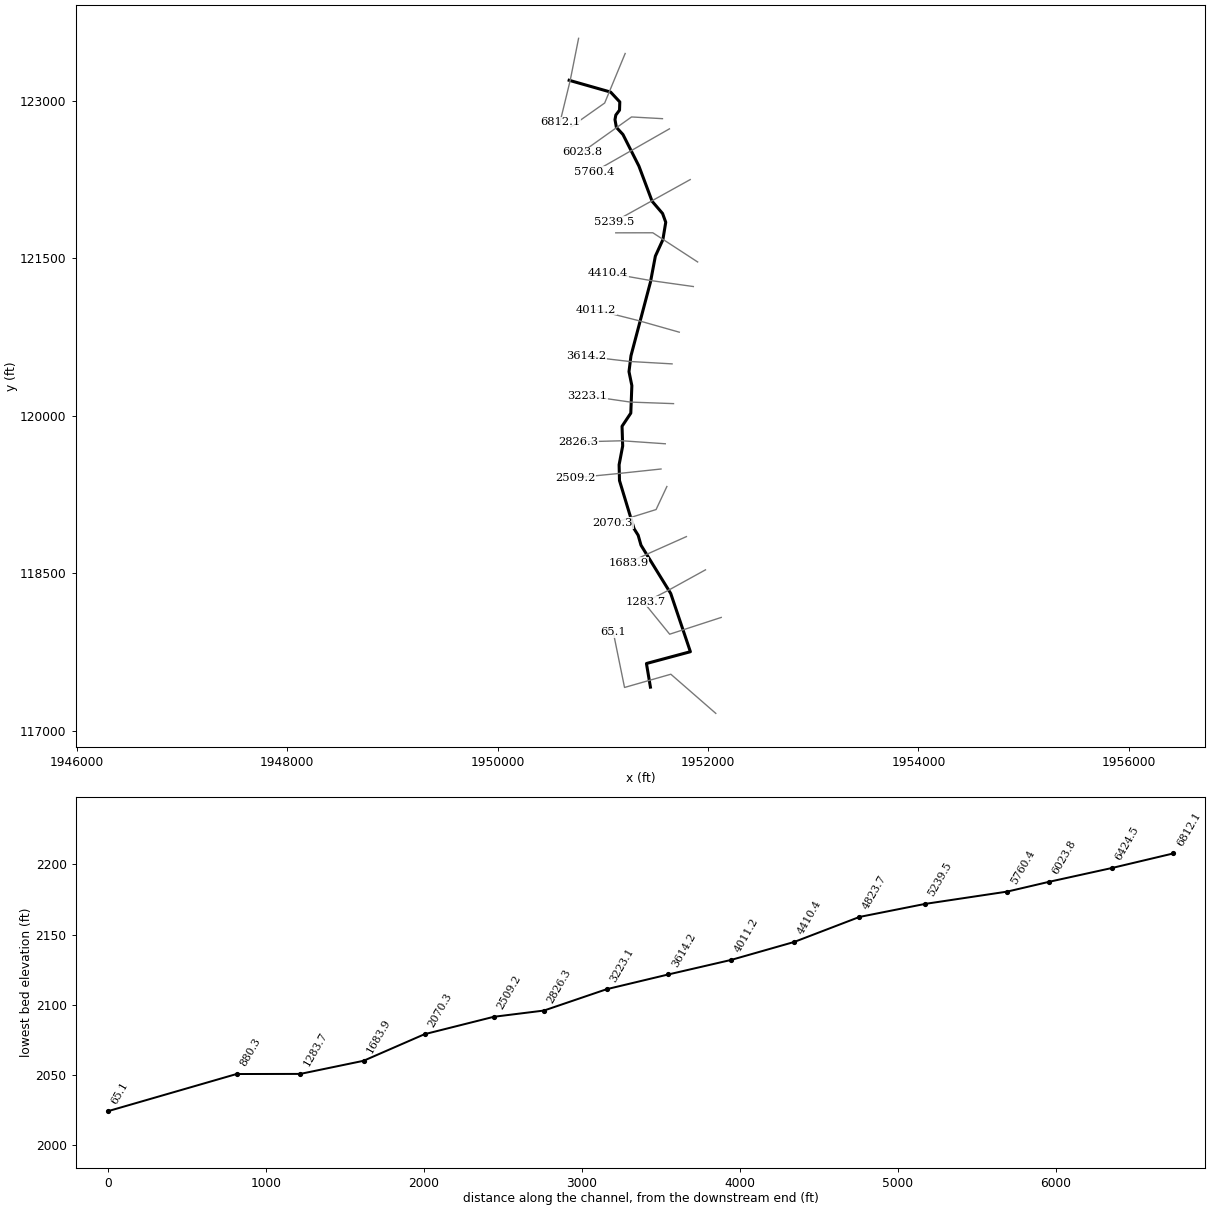
--- NP345.prj (project) ---

Proj Title=NP345
Current Plan=p01
Default Exp/Contr=0,0
English Units
Geom File=g01
Flow File=f01
Plan File=p01
BEGIN DESCRIPTION:
END DESCRIPTION:
DSS Export Rating Curves= 0
DSS Export Rating Curve Sorted= 0
DSS Export Volume Flow Curves= 0
DXF OffsetX= 0
DXF OffsetY= 0
DXF ScaleX= 0
DXF ScaleY= 0

--- NP345.p01 (plan) ---

Plan Title=Floodplain
Program Version=4.00
Geom File=g01
Flow File=f01
K Sum by GR=0
Std Step Tol=0.01
Critical Tol=0.01
Num of Std Step Trials=20
Max Error Tol=0.3
Flow Tol Ratio=0.001
Split Flow NTrial=30
Split Flow Tol=0.02
Split Flow Ratio=0.02
Log Output Level=0
Friction Slope Method=1
Unsteady Friction Slope Method=2
Unsteady Bridges Friction Slope Method=1
Global Log Level=0
CheckData=False
Run HTab=0
Run UNet=0
Run PostProcess=0
UNET Theta=0
UNET Theta Warmup=0
UNET ZTol=0
UNET ZSATol=0
UNET MxIter=0
UNET MaxInSteps=0
UNET DtIC=0
UNET DtMin=0
UNET MaxCRTS=0
UNET WFStab=0
UNET SFStab=0
UNET WFX=0
UNET SFX=0
UNET DSS MLevel=0
UNET DZMax Abort=0
UNET Convert EG Bridges=0
UNET Use Existing IB Tables=0
UNET Froude Limit=0
UNET Froude Power=0
Write IC File=0
Echo Input=False
Echo Output=False
Write Detailed=0

--- NP345.f01 (steady flow) ---

Flow Title=NFF Regression Equation
Program Version=4.00
Number of Profiles=1
Profile Names=P100yr
River Rch & RM=NP345,Main      ,6812.1
393.1761
River Rch & RM=NP345,Main      ,6424.5
393.1761
River Rch & RM=NP345,Main      ,6023.8
582.3001
River Rch & RM=NP345,Main      ,5239.5
635.9109
River Rch & RM=NP345,Main      ,2070.3
682.6304
River Rch & RM=NP345,Main      ,1683.9
788.7079
River Rch & RM=NP345,Main      ,65.1
820.1937
Boundary for River Rch & Prof#=NP345,Main      ,1
Up Type=0
Dn Type=3
Dn Slope=0.019435

--- NP345.g01 (geometry) ---

Geom Title=USGS 3m DEM
Program Version=4.10

River Reach=NP345           ,Main
Reach XY= 30
      1950680.11       123195.25     1951074.136      123082.931
     1951161.376      122989.181     1951158.772      122911.056
     1951123.616      122864.181     1951115.793      122820.687
     1951128.824      122746.994     1951191.317       122679.08
     1951343.222      122377.843     1951468.523      122043.136
     1951568.077      121926.417     1951598.115       121843.17
     1951570.652      121676.674     1951499.419      121520.477
     1951453.043      121274.337     1951267.674      120572.028
     1951248.818      120420.234      1951275.96      120287.358
     1951265.982      120025.451     1951182.734       119900.15
     1951188.742      119712.199     1951154.866      119533.452
     1951158.379      119383.548     1951297.265      118924.171
     1951335.912      118862.368     1951362.828      118767.392
     1951645.468      118307.699     1951832.217      117753.134
     1951414.642       117640.68     1951452.448       117415.72

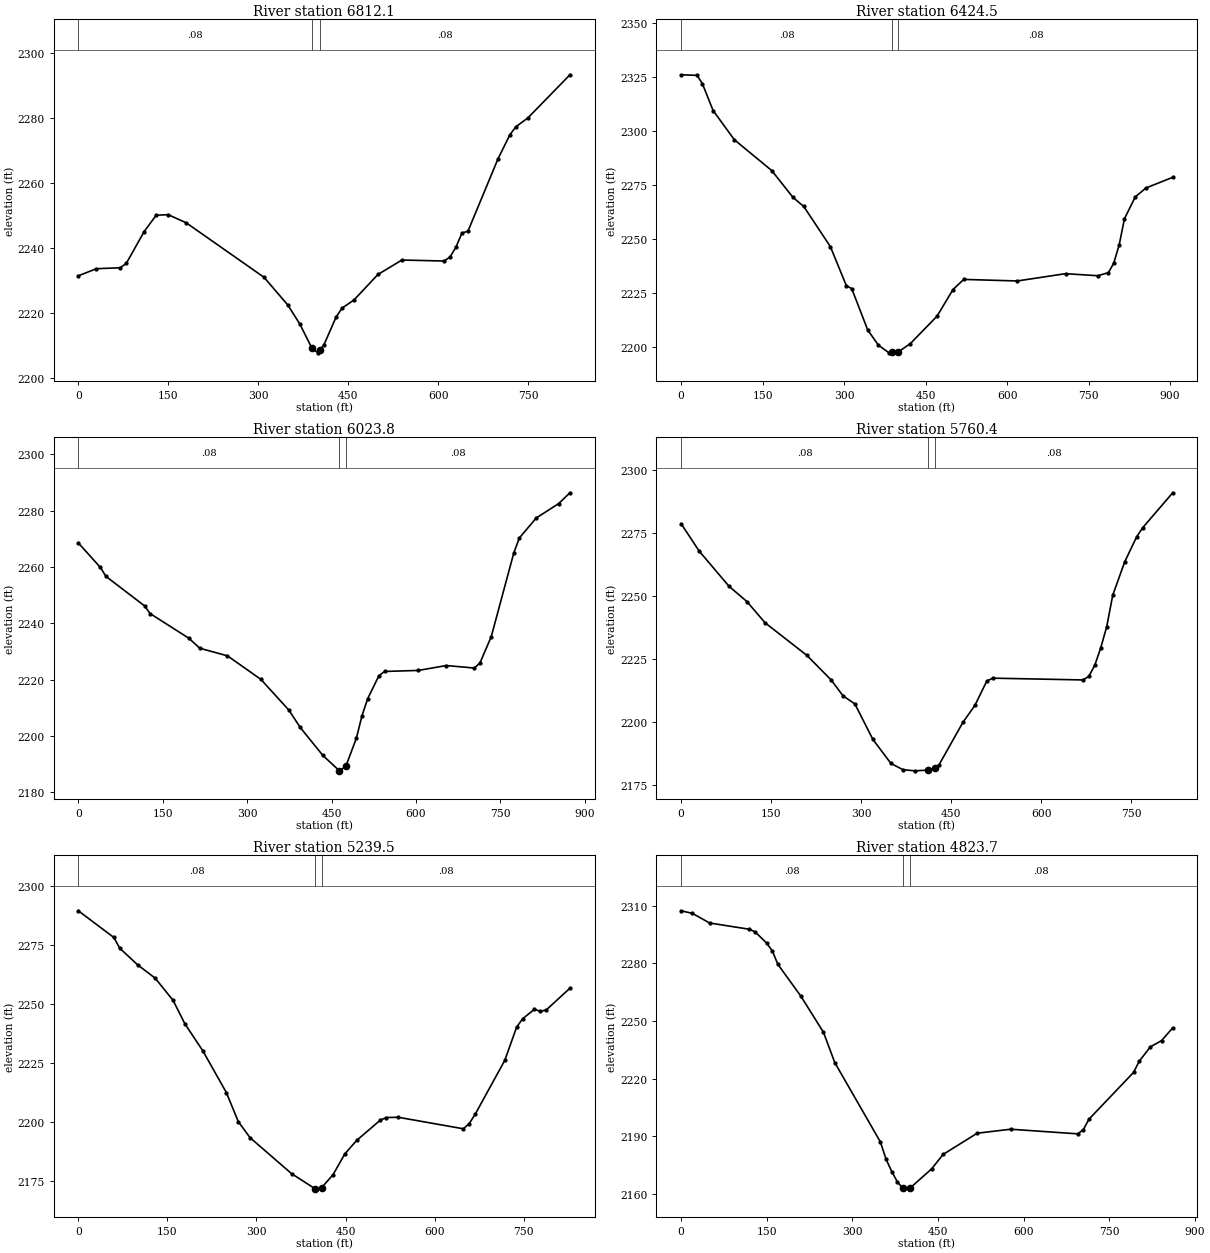
Type RM Length L Ch R = 1 ,6812.1  ,391.7,387.6,384.3
XS GIS Cut Line= 3
     1950769.826      123594.846     1950689.917      123193.299
     1950592.904      122794.994
#Sta/Elev= 30
       0 2231.51      30 2233.69    69.9 2233.99    79.9 2235.31   109.8 2245.13
   129.8 2250.15   149.8 2250.32   179.8 2247.82   309.6 2231.04   349.5 2222.45
   369.5 2216.58   389.4 2209.23   399.4 2207.82   403.4 2208.81   409.4  2210.3
   429.4 2218.72   439.4 2221.55   459.4 2224.07   499.4 2231.92   539.4 2236.37
   609.4 2236.06   619.4 2237.26   629.4 2240.32   639.4 2244.66   649.4 2245.22
   699.4 2267.45   719.4 2274.92   729.4 2277.36   749.4 2280.09   819.4 2293.34
#Mann= 3 , 0 , 0
       0     .08       0   389.4    .045       0   403.4     .08       0
Bank Sta=389.4,403.4
XS Rating Curve= 0 ,0
Exp/Cntr=0.3,0.1

Type RM Length L Ch R = 1 ,6424.5  ,413.2,400.7,388.1
XS GIS Cut Line= 3
     1951212.395      123450.468     1951017.685      122978.818
     1950695.692      122751.021
#Sta/Elev= 30
       0 2325.95    29.4 2325.69    39.2 2321.86    58.9 2309.44    98.1 2295.92
   166.8  2281.7   206.1 2269.25   225.7 2265.13   274.8 2246.52   304.2 2228.46
     314 2227.16   343.4 2208.08   363.1 2201.01   382.7 2197.47   387.8 2197.64
   399.8  2197.9     422 2201.76     471 2214.41   500.4 2226.71   520.1  2231.4
   618.7 2230.68   707.5 2234.05   766.6  2233.1   786.4 2234.52   796.2  2238.9
   806.1 2247.25   815.9 2259.41   835.7 2269.49   855.4 2273.64   904.7 2278.57
#Mann= 3 , 0 , 0
       0     .08       0   387.8    .045       0   399.8     .08       0
Bank Sta=387.8,399.8
XS Rating Curve= 0 ,0
Exp/Cntr=0.3,0.1

Type RM Length L Ch R = 1 ,6023.8  ,265.8,263.4,261.1
XS GIS Cut Line= 3
     1951566.817      122829.792     1951272.864      122846.079
     1950801.683      122509.653
#Sta/Elev= 30
       0 2268.53    39.2 2259.82    49.1 2256.64   117.8 2246.14   127.6 2243.41
   196.3 2234.68   215.9  2231.1     265 2228.41   324.4 2220.04   374.3 2209.07
   394.2 2202.98   434.2 2193.07   463.3 2187.67   464.1 2187.55   475.3 2189.17
     494 2199.15     504 2207.14     514 2213.16     534 2221.33     544 2222.86
   603.8 2223.22   653.8 2224.96   703.7 2224.07   713.6  2225.9   733.6 2235.23
   773.5 2264.85   783.5 2270.28   813.5 2277.37   853.4 2282.51   873.4 2286.34
#Mann= 3 , 0 , 0
       0     .08       0   463.3    .045       0   475.3     .08       0
Bank Sta=463.3,475.3
XS Rating Curve= 0 ,0
Exp/Cntr=0.3,0.1

Type RM Length L Ch R = 1 ,5760.4  ,521,520.7,520.3
XS GIS Cut Line= 3
     1951633.106      122732.823     1951277.559      122529.655
     1950922.013      122326.488
#Sta/Elev= 30
       0 2278.71      30 2267.85    79.9 2253.83   109.9 2247.74   139.8 2239.38
   209.7  2226.4   249.7 2216.74   269.7 2210.41   289.6 2207.13   319.6 2193.05
   349.6 2183.55   369.6 2181.07   389.5 2180.61   411.8 2180.91   423.8 2181.84
   429.5 2182.92   469.4  2199.8   489.4 2206.55   509.4 2216.29   519.4 2217.38
   669.2 2216.68   679.2 2218.06   689.2 2222.53   699.2 2229.46   709.1 2237.87
   719.1  2250.3   739.1 2263.57   759.1 2273.55   769.1 2277.11     819 2290.94
#Mann= 3 , 0 , 0
       0     .08       0   411.8    .045       0   423.8     .08       0
Bank Sta=411.8,423.8
XS Rating Curve= 0 ,0
Exp/Cntr=0.3,0.1

Type RM Length L Ch R = 1 ,5239.5  ,438.2,414.9,391.3
XS GIS Cut Line= 2
     1951830.636      122249.535     1951107.005      121847.537
#Sta/Elev= 30
       0  2289.6    59.8  2278.3    69.8 2273.73    99.7 2266.75   129.6 2261.01
   159.6 2251.64   179.5  2241.7   209.4 2230.38   249.3  2212.6   269.3 2200.32
   289.2 2193.49     359 2178.27   398.9 2171.82   409.7 2172.31   428.9 2177.81
   448.8 2186.63   468.8 2192.36   508.6 2200.94   518.6 2202.03   538.6 2202.14
   648.3 2197.26   658.2 2199.44   668.2  2203.4   718.1 2226.23     738 2240.29
     748 2243.82     768 2247.88   777.9    2247   787.9  2247.6   827.8  2256.8
#Mann= 3 , 0 , 0
       0     .08       0   398.9    .045       0   409.7     .08       0
Bank Sta=398.9,409.7
XS Rating Curve= 0 ,0
Exp/Cntr=0.3,0.1

Type RM Length L Ch R = 1 ,4823.7  ,403.4,413.1,422.5
XS GIS Cut Line= 3
      1951901.26      121464.977     1951475.405      121742.975
     1951123.134       121742.48
#Sta/Elev= 30
       0 2307.36    19.9    2306    49.9    2301   119.7 2297.73   129.6 2296.38
   149.6 2290.61   159.6 2286.55   169.5 2279.45   209.4 2263.04   249.3 2244.08
   269.2 2228.24     349 2186.96     359 2177.89     369  2171.5   378.9 2166.02
   388.4 2162.91   398.9 2162.54   400.4 2162.82   438.8 2172.96   458.7 2180.44
   518.4 2191.51   577.1 2193.59   694.5 2191.18   704.3 2193.33     714 2198.76
   792.3  2223.2   802.1 2228.96   821.7  2236.5   841.3 2239.75   860.8 2246.36
#Mann= 3 , 0 , 0
       0     .08       0   388.4    .045       0   400.4     .08       0
Bank Sta=388.4,400.4
XS Rating Curve= 0 ,0
Exp/Cntr=0.3,0.1

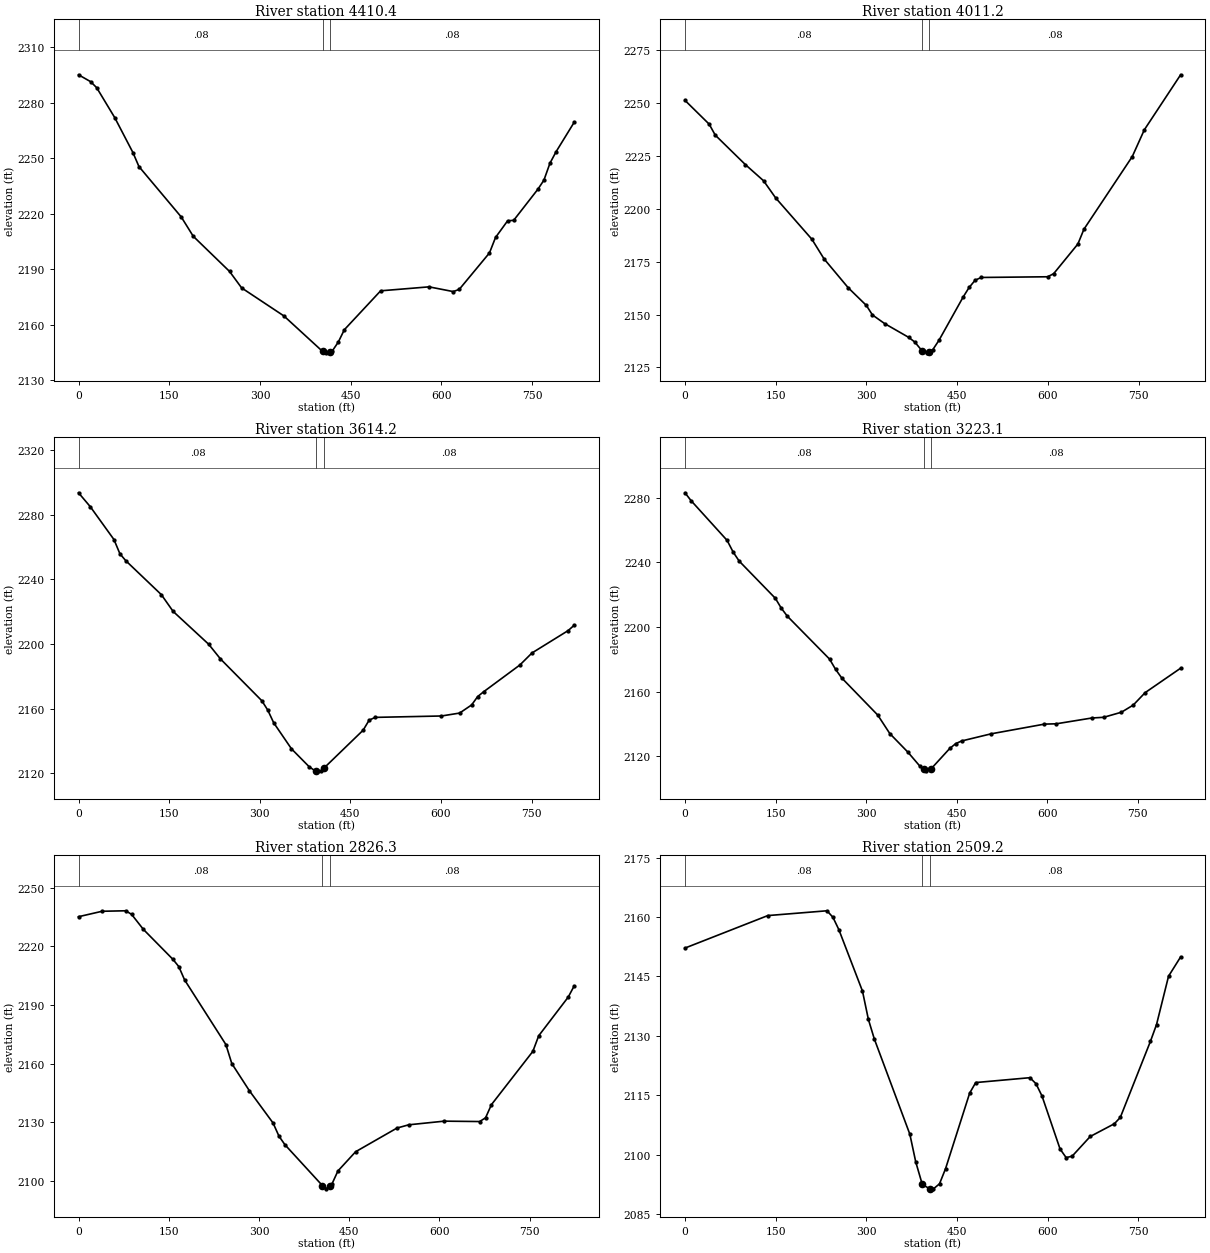
Type RM Length L Ch R = 1 ,4410.4  ,401.9,399,397.2
XS GIS Cut Line= 3
     1951860.423      121230.993     1951454.981      121288.097
     1951051.469      121359.712
#Sta/Elev= 30
       0 2295.18      20 2291.46      30 2288.21    59.9 2271.98    89.9 2253.12
    99.9 2245.51   169.8 2218.25   189.7 2207.77   249.7 2188.75   269.6 2179.86
   339.5 2164.68   403.4 2145.49   409.4 2144.71   415.4  2145.3   419.4 2145.69
   429.4 2150.53   439.4 2157.21   499.4 2178.27   579.4 2180.42   619.4 2177.86
   629.4 2179.07   679.3 2198.78   689.3 2207.13   709.3 2216.16   719.3 2216.41
   759.3 2233.23   769.3 2238.15   779.3 2247.34   789.3 2253.48   819.3 2269.46
#Mann= 3 , 0 , 0
       0     .08       0   403.4    .045       0   415.4     .08       0
Bank Sta=403.4,415.4
XS Rating Curve= 0 ,0
Exp/Cntr=0.3,0.1

Type RM Length L Ch R = 1 ,4011.2  ,392.4,397,400.8
XS GIS Cut Line= 3
     1951726.575      120796.265     1951332.461       120908.21
     1950935.535      121008.764
#Sta/Elev= 30
       0 2251.39      40 2240.13      50 2234.95    99.9 2220.97   129.9 2213.34
   149.9 2205.21   209.8 2185.65   229.8  2176.4   269.8 2162.71   299.8 2154.34
   309.8 2149.85   329.8 2145.79   369.7 2139.24   379.7 2137.05   391.6 2132.97
   399.7 2131.91   403.6 2132.51   409.7 2133.46   419.7  2137.8   459.6 2158.25
   469.6 2162.84   479.6 2166.28   489.6 2167.58   599.5 2167.91   609.4 2169.39
   649.4 2183.42   659.4 2190.42   739.3 2224.81   759.2 2237.46   819.2  2263.5
#Mann= 3 , 0 , 0
       0     .08       0   391.6    .045       0   403.6     .08       0
Bank Sta=391.6,403.6
XS Rating Curve= 0 ,0
Exp/Cntr=0.3,0.1

Type RM Length L Ch R = 1 ,3614.2  ,390.5,391.1,390.7
XS GIS Cut Line= 3
     1951658.391      120494.324     1951247.854       120517.86
     1950841.458      120565.671
#Sta/Elev= 30
       0 2293.56    19.6  2284.9    58.7 2264.61    68.5 2255.85    78.3 2251.52
   137.1 2230.55   156.6 2220.19   215.4 2199.89     235 2190.77   303.5  2164.9
   313.3 2159.09   323.1 2151.27   352.5 2135.18   381.8  2124.1   391.6 2121.57
   393.9  2121.6   401.4  2121.7   405.9 2123.14   471.1 2146.71   481.1 2152.94
   491.1 2154.64   600.8  2155.5   630.8  2157.3   650.7 2162.34   660.7 2167.52
   670.7 2170.52   730.6 2187.06   750.6 2194.48   810.4 2208.31   820.4 2211.62
#Mann= 3 , 0 , 0
       0     .08       0   393.9    .045       0   405.9     .08       0
Bank Sta=393.9,405.9
XS Rating Curve= 0 ,0
Exp/Cntr=0.3,0.1

Type RM Length L Ch R = 1 ,3223.1  ,397.8,396.7,399.3
XS GIS Cut Line= 3
     1951671.981      120115.823     1951263.147      120130.425
     1950855.551      120189.082
#Sta/Elev= 30
       0 2283.03      10  2278.2    69.8 2253.57    79.8 2246.34    89.8 2240.76
   149.7 2217.75   159.6  2211.6   169.6 2206.66   239.5 2180.14   249.4 2173.82
   259.4 2168.58   319.3 2145.52   339.2 2134.11   369.2  2122.6   389.1 2113.91
   395.2 2112.16   399.1 2111.04   407.2 2112.11   438.5 2124.88   448.3 2127.84
   458.1 2129.51   507.1 2133.94   595.4 2139.94     615 2140.14   673.8 2143.72
   693.4 2144.15   722.8 2147.29   742.4 2151.72   762.1  2159.4   820.9 2174.53
#Mann= 3 , 0 , 0
       0     .08       0   395.2    .045       0   407.2     .08       0
Bank Sta=395.2,407.2
XS Rating Curve= 0 ,0
Exp/Cntr=0.3,0.1

Type RM Length L Ch R = 1 ,2826.3  ,313.2,317.1,318.6
XS GIS Cut Line= 3
     1951593.623      119733.488      1951183.08      119762.111
     1950770.897      119751.261
#Sta/Elev= 30
       0 2235.21    39.2    2238    78.4 2238.25    88.2 2236.43   107.8 2228.73
   156.8 2213.42   166.6 2209.71   176.4 2202.81     245 2169.72   254.8    2160
   284.2    2146   323.4 2129.55   333.2 2122.82     343 2118.47   405.5 2097.47
   411.5 2095.83   417.5 2097.38   421.4 2098.39   431.2 2104.98   460.6 2114.83
   529.4 2126.97     549 2128.63   607.9  2130.5   666.8  2130.3   676.6 2132.21
   686.4 2138.96   755.2 2166.23     765 2174.25     814 2194.03   823.9 2199.75
#Mann= 3 , 0 , 0
       0     .08       0   405.5    .045       0   417.5     .08       0
Bank Sta=405.5,417.5
XS Rating Curve= 0 ,0
Exp/Cntr=0.3,0.1

Type RM Length L Ch R = 1 ,2509.2  ,434.4,438.6,442.8
XS GIS Cut Line= 3
     1951553.252      119493.231     1951144.316      119449.773
     1950737.336      119409.689
#Sta/Elev= 30
       0 2152.15   137.1 2160.35     235 2161.56   244.8 2159.93   254.6 2156.81
   293.7  2141.3   303.5 2134.15   313.3 2129.22   372.1 2105.18   381.9 2098.16
   392.7  2092.5   404.7 2091.43   411.2 2091.39   421.2 2092.66   431.2 2096.48
   471.1 2115.55   481.1 2118.21   570.8 2119.44   580.8 2117.93   590.8 2114.82
   620.7 2101.44   630.7 2099.28   640.6 2099.62   670.6  2104.6   710.5 2107.81
   720.4 2109.42   770.3 2128.64   780.3 2132.84   800.2 2145.05   820.2 2149.92
#Mann= 3 , 0 , 0
       0     .08       0   392.7    .045       0   404.7     .08       0
Bank Sta=392.7,404.7
XS Rating Curve= 0 ,0
Exp/Cntr=0.3,0.1

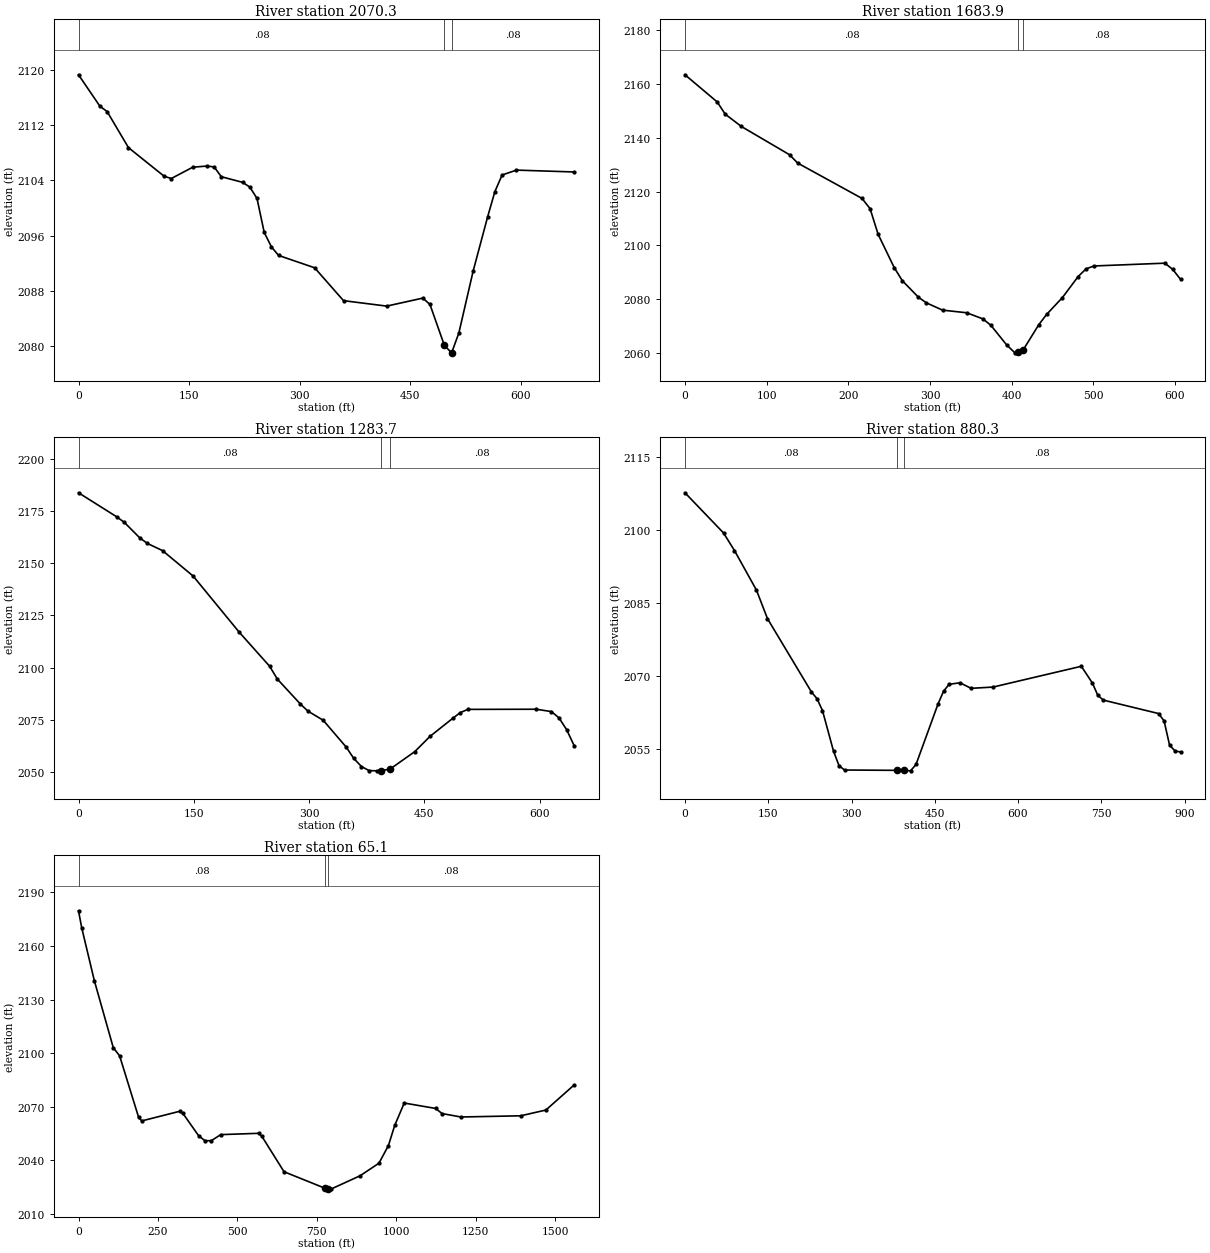
Type RM Length L Ch R = 1 ,2070.3  ,383.7,386.2,389.2
XS GIS Cut Line= 3
     1951608.848      119326.441     1951506.272      119107.039
     1951095.535      118978.562
#Sta/Elev= 30
       0 2119.32    29.1 2114.75    38.8 2113.99    67.8 2108.75   116.2  2104.6
   125.9 2104.27     155 2105.91   174.4 2106.08   184.1 2105.95   193.8 2104.53
   222.8 2103.71   232.5 2103.02   242.2 2101.39     252 2096.45   261.8 2094.35
   271.5 2093.11   320.4 2091.32   359.6 2086.55   418.2 2085.76   467.2 2086.92
   476.9    2086   496.5 2080.05   506.3 2078.98   516.1 2081.85   535.6 2090.88
   555.2 2098.72     565 2102.37   574.8 2104.78   594.3 2105.49   672.6 2105.22
#Mann= 3 , 0 , 0
       0     .08       0   496.5    .045       0   506.3     .08       0
Bank Sta=496.5,506.3
XS Rating Curve= 0 ,0
Exp/Cntr=0.3,0.1

Type RM Length L Ch R = 1 ,1683.9  ,398.4,400.2,401
XS GIS Cut Line= 3
     1951794.392      118849.347     1951416.415      118680.588
     1951242.212       118597.32
#Sta/Elev= 30
       0 2163.41    39.4 2153.33    49.3 2148.76      69  2144.2   128.1 2133.67
     138 2130.58   216.8 2117.44   226.7 2113.62   236.5 2104.12   256.2 2091.74
   266.1 2086.87   285.8 2080.72   295.7  2078.6   315.4  2075.9     345 2074.92
   364.7 2072.66   374.5  2070.3   394.2 2062.87   404.1 2060.02   407.9 2060.39
   413.9 2060.98   433.2 2070.44   442.9 2074.32   462.2 2080.56   481.5  2088.4
   491.2 2091.24   500.8 2092.32   587.7 2093.36   597.4 2091.02     607  2087.3
#Mann= 3 , 0 , 0
       0     .08       0   407.9    .045       0   413.9     .08       0
Bank Sta=407.9,413.9
XS Rating Curve= 0 ,0
Exp/Cntr=0.3,0.1

Type RM Length L Ch R = 1 ,1283.7  ,407.4,403.4,399.9
XS GIS Cut Line= 3
     1951975.716       118532.81       1951618.6      118335.584
     1951407.675      118227.462
#Sta/Elev= 30
       0  2183.7    49.8 2172.18    59.7 2169.52    79.6 2162.17    89.6 2159.47
   109.4 2156.02   149.2 2143.85     209 2117.06   248.8 2100.67   258.7 2094.59
   288.6 2082.69   298.5 2079.26   318.4 2074.88   348.3 2062.06   358.2 2056.61
   368.2 2052.75   378.1  2050.8   388.1 2050.68   393.6 2050.72   405.6 2051.56
   437.6 2059.88   457.3 2067.13     487  2075.8   496.8 2078.54   506.7 2080.08
   595.6 2080.15   615.4 2079.03   625.2 2076.03   635.1 2070.44     645 2062.71
#Mann= 3 , 0 , 0
       0     .08       0   393.6    .045       0   405.6     .08       0
Bank Sta=393.6,405.6
XS Rating Curve= 0 ,0
Exp/Cntr=0.3,0.1

Type RM Length L Ch R = 1 ,880.3   ,812.8,815.1,806.2
XS GIS Cut Line= 3
     1952125.383      118079.552      1951635.43      117919.895
     1951397.645      118213.177
#Sta/Elev= 30
       0 2107.62    69.4 2099.39    89.2 2095.77   128.8 2087.65   148.6 2081.81
   227.9 2066.76   237.8 2065.41   247.7 2062.96   267.6 2054.63   277.5 2051.66
   287.4 2050.77   382.1  2050.7   394.1  2050.7   406.3  2050.6   416.2  2051.9
   455.8 2064.29   465.8 2066.92   475.7 2068.34   495.5 2068.66   515.3 2067.52
     555 2067.78     714 2072.04   733.9 2068.61   743.8 2066.06   753.8  2065.1
   853.1 2062.35   863.1 2060.84     873 2055.85   882.9 2054.68   892.9 2054.46
#Mann= 3 , 0 , 0
       0     .08       0   382.1    .045       0   394.1     .08       0
Bank Sta=382.1,394.1
XS Rating Curve= 0 ,0
Exp/Cntr=0.3,0.1

Type RM Length L Ch R = 1 ,65.1    ,67.5,65.1,62.8
XS GIS Cut Line= 4
     1952073.664      117165.822     1951646.563      117538.697
     1951206.443      117412.557     1951099.861      117936.414
#Sta/Elev= 30
       0 2179.69      10 2170.24    49.7 2140.64   109.4 2103.07   129.3 2098.52
     189 2064.16   198.9 2062.09   318.3 2067.48   328.2 2066.36     378 2053.78
   397.9 2051.02   417.8 2051.03   447.6 2054.42     567 2055.16   576.9 2053.45
   646.6 2033.65   774.1 2024.51   786.1 2024.12   795.9 2024.08   885.5 2031.36
   945.2 2038.42     975 2048.28     995 2059.66  1024.8  2072.1  1123.8 2069.06
  1143.6 2066.21    1203 2064.29  1391.1 2064.95  1470.3 2068.17  1559.4 2082.22
#Mann= 3 , 0 , 0
       0     .08       0   774.1    .045       0   786.1     .08       0
Bank Sta=774.1,786.1
XS Rating Curve= 0 ,0
Exp/Cntr=0.3,0.1

Chan Stop Cuts=-1
Use User Specified Reach Order=0
Composite Channel Slope=5